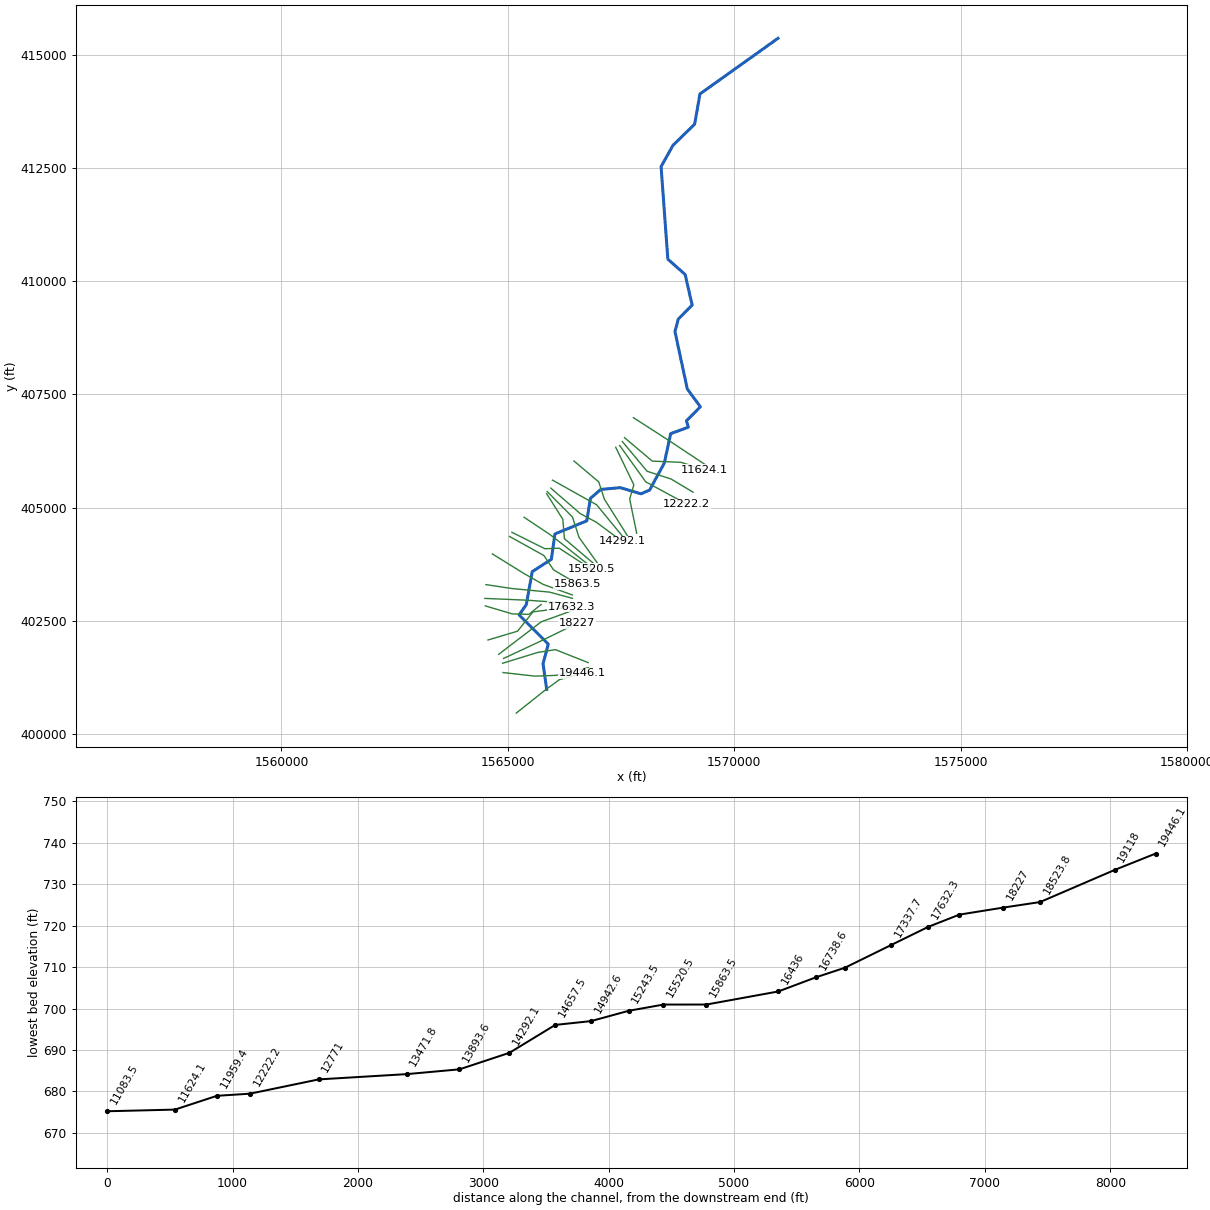
--- BRUSHCR.prj (project) ---

Proj Title=BRUSHCR
Current Plan=p01
Default Exp/Contr=0,0
English Units
Geom File=g01
Flow File=f01
Plan File=p01
BEGIN DESCRIPTION:
END DESCRIPTION:
DSS Export Rating Curves= 0
DSS Export Rating Curve Sorted= 0
DSS Export Volume Flow Curves= 0
DXF OffsetX= 0
DXF OffsetY= 0
DXF ScaleX= 0
DXF ScaleY= 0

--- BRUSHCR.p01 (plan) ---

Plan Title=Floodplain
Program Version=4.00
Geom File=g01
Flow File=f01
K Sum by GR=0
Std Step Tol=0.01
Critical Tol=0.01
Num of Std Step Trials=20
Max Error Tol=0.3
Flow Tol Ratio=0.001
Split Flow NTrial=30
Split Flow Tol=0.02
Split Flow Ratio=0.02
Log Output Level=0
Friction Slope Method=1
Unsteady Friction Slope Method=2
Unsteady Bridges Friction Slope Method=1
Global Log Level=0
CheckData=False
Run HTab=0
Run UNet=0
Run PostProcess=0
UNET Theta=0
UNET Theta Warmup=0
UNET ZTol=0
UNET ZSATol=0
UNET MxIter=0
UNET MaxInSteps=0
UNET DtIC=0
UNET DtMin=0
UNET MaxCRTS=0
UNET WFStab=0
UNET SFStab=0
UNET WFX=0
UNET SFX=0
UNET DSS MLevel=0
UNET DZMax Abort=0
UNET Convert EG Bridges=0
UNET Use Existing IB Tables=0
UNET Froude Limit=0
UNET Froude Power=0
Write IC File=0
Echo Input=False
Echo Output=False
Write Detailed=0

--- BRUSHCR.f01 (steady flow) ---

Flow Title=NFF Regression Equation
Program Version=4.00
Number of Profiles= 1
Profile Names=P100yr
River Rch & RM=BRUSHCR,Main            ,19446.1
     363
River Rch & RM=BRUSHCR,Main            ,18523.8
     368
River Rch & RM=BRUSHCR,Main            ,18227
     407
River Rch & RM=BRUSHCR,Main            ,17632.3
     412
River Rch & RM=BRUSHCR,Main            ,17337.7
     540
River Rch & RM=BRUSHCR,Main            ,16738.6
     543
River Rch & RM=BRUSHCR,Main            ,16436
     602
River Rch & RM=BRUSHCR,Main            ,15243.5
     613
River Rch & RM=BRUSHCR,Main            ,14942.6
     746
River Rch & RM=BRUSHCR,Main            ,14657.5
     755
River Rch & RM=BRUSHCR,Main            ,11959.4
     838
Boundary for River Rch & Prof#=BRUSHCR,Main            , 1
Up Type= 0
Dn Type= 3
Dn Slope=0.004204
DSS Import GetInterval= 0
DSS Import GetPeak= 0
DSS Import FillOption= 0

--- BRUSHCR.g01 (geometry) ---

Geom Title=USGS 10m DEM
Program Version=4.00

River Reach=BRUSHCR         ,Main
Reach XY= 30
     1565858.679       400985.23     1565778.334      401553.177
     1565892.849      401986.251     1565248.281      402630.979
     1565408.548      402860.549     1565539.317       403586.97
     1565961.552      403859.167     1566040.152      404419.282
     1566743.838      404708.769     1566823.662       405204.73
     1567053.076      405402.193     1567482.621       405441.64
      1567941.61      405305.802     1568130.403       405388.01
     1568455.966       405985.45     1568594.824       406633.68
       1568985.9       406776.11     1568945.253      406918.906
     1569251.738      407227.139     1568963.433       407620.29
     1568690.448      408888.359     1568763.591      409163.377
     1569070.792      409472.041     1568915.728      410147.883
     1568533.639      410486.394     1568384.271      412529.534
     1568645.665      412998.976     1569125.776      413468.418
     1569243.137      414135.239     1570965.141      415363.393

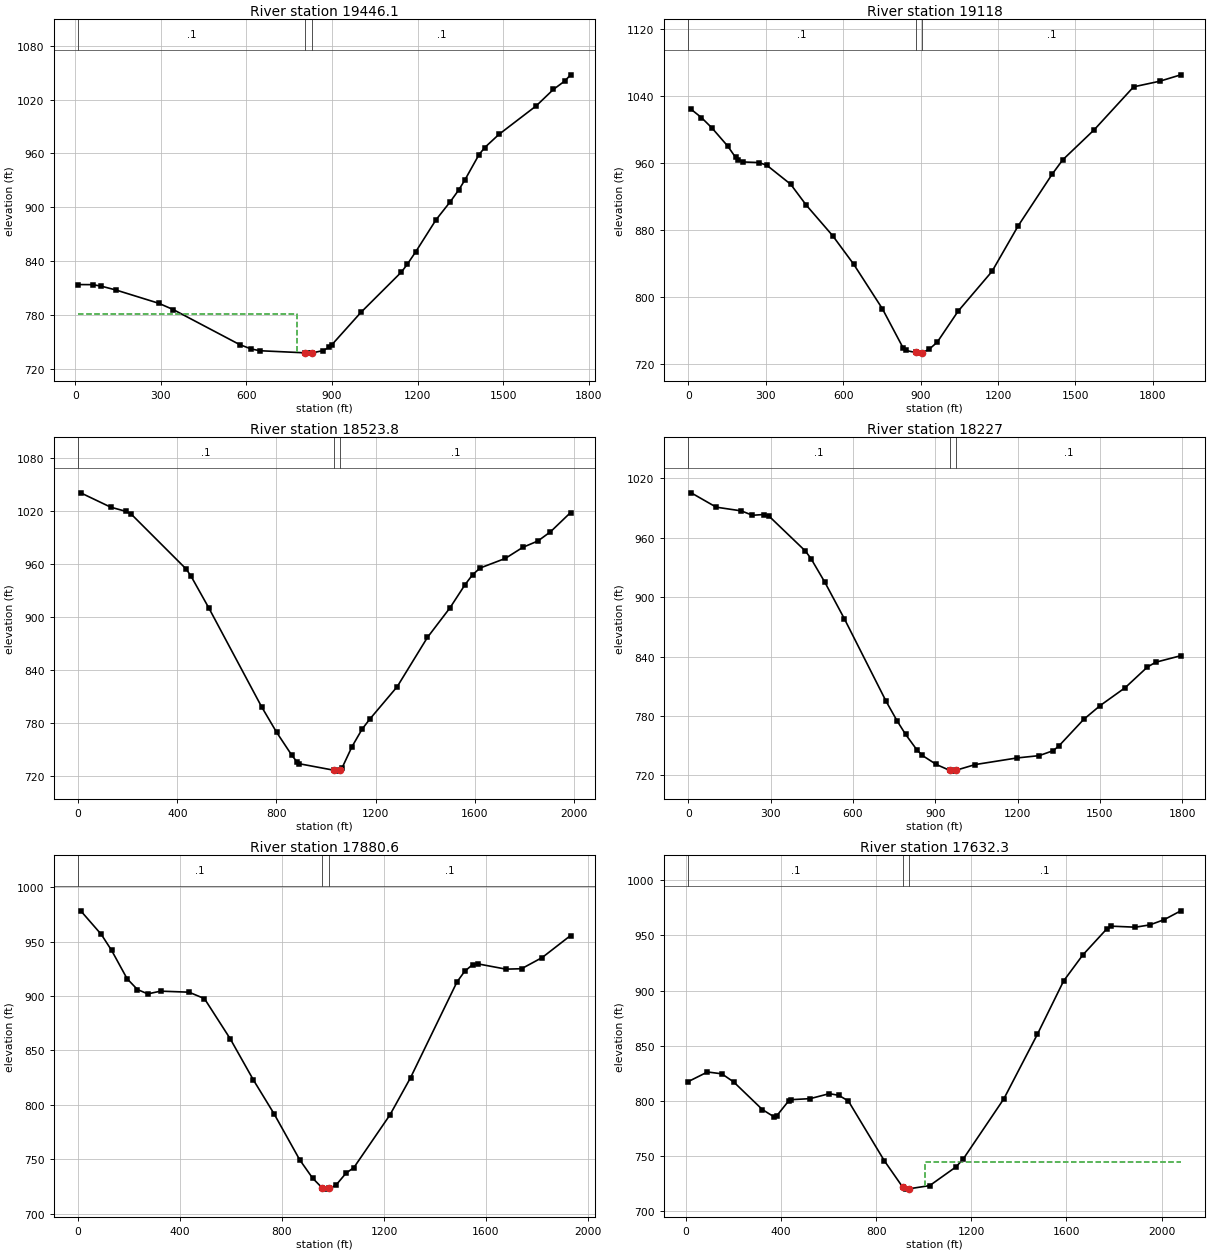
Type RM Length L Ch R = 1 ,19446.1 ,346.3,328.1,307.9
XS GIS Cut Line= 4
      1565187.47      400464.216      1565851.52      400992.212
     1566138.754      401201.581     1566651.536      401342.655
#Sta/Elev= 30
    10.1  813.82    60.6  813.72    90.9  812.06   141.4  807.87   292.9  792.92
   343.4  785.92   575.7  746.97   616.1  742.09   646.4  740.09   805.6  737.74
   818.1  737.41   830.6  737.72   868.7  740.25     889  743.93   899.2  746.76
  1000.7  782.73  1142.9  827.79  1163.2  836.31  1193.7  850.67    1264  885.96
  1314.2  906.19  1344.3  919.53  1364.4  929.92  1414.5  958.47  1434.6  966.46
  1484.8  981.23  1615.2 1012.97  1675.4 1031.28  1715.6 1040.74  1735.7 1047.57
#Mann= 3 , 0 , 0
    10.1      .1       0   805.6    .045       0   830.6      .1       0
#XS Ineff= 2 , 0
          775.28  780.83
Permanent Ineff=
       F       F
Bank Sta=805.6,830.6
XS Rating Curve= 0 ,0
Exp/Cntr=0.3,0.1

Type RM Length L Ch R = 1 ,19118   ,590.8,594.2,600.5
XS GIS Cut Line= 4
     1564893.871      401358.825     1565600.854      401279.499
      1566065.91      401296.723     1566777.368      401467.633
#Sta/Elev= 30
    10.2 1024.47    50.8 1014.44    91.5 1002.08   152.4  980.49   182.9  967.02
   193.1  964.39   213.4  961.53   274.4   960.8   304.9  957.38   396.4  934.96
   457.3  909.87     559  873.65   640.3  839.71   751.9   786.4   832.8  739.37
   842.9   736.6     881   734.2   893.5  733.44     906  733.68     934  738.29
   964.3  746.43  1045.3  783.42  1176.8  830.95  1278.4  885.38  1410.5   947.2
  1451.2  964.17  1573.1    1000  1725.6 1051.16  1827.2 1057.89  1908.5  1065.5
#Mann= 3 , 0 , 0
       0      .1       0     881    .045       0     906      .1       0
Bank Sta=881,906
XS Rating Curve= 0 ,0
Exp/Cntr=0.3,0.1

Type RM Length L Ch R = 1 ,18523.8 ,285.7,296.7,306.9
XS GIS Cut Line= 4
     1564883.395      401563.431     1565658.268      401801.969
     1566048.685      401865.125     1566774.632      401578.281
#Sta/Elev= 30
    10.1 1040.67   131.7 1024.39   192.6 1019.71   212.8 1016.92   435.8  954.42
   456.1     946     527  910.44   739.8  798.67   800.6   769.7   861.5  743.88
   881.7  736.54   891.9  734.07  1031.5  726.73    1044   725.7  1056.5   726.6
  1064.3  729.06  1104.8  753.36  1145.4  773.13  1175.8  784.27  1287.3  821.31
    1409  876.94  1500.2  910.52  1561.1  936.79  1591.5  948.02  1621.9  955.59
  1723.2   966.4  1794.2     979    1855  986.16  1905.7  996.56  1986.8 1018.36
#Mann= 3 , 0 , 0
       0      .1       0  1031.5    .045       0  1056.5      .1       0
Bank Sta=1031.5,1056.5
XS Rating Curve= 0 ,0
Exp/Cntr=0.3,0.1

Type RM Length L Ch R = 1 ,18227   ,340.3,346.4,352.3
XS GIS Cut Line= 3
      1564906.14      401669.916     1565789.211      402083.266
     1566525.224       402445.01
#Sta/Elev= 30
    10.2 1005.42   101.6  990.93     193  987.19   233.6  982.74   274.2   983.5
   294.5  981.73   426.6  946.63   446.9  939.04   497.7  915.02   568.8  878.16
   721.1  794.72   761.7  774.72   792.2  761.35   832.8  745.92   853.1  740.16
   903.9  731.06   952.4  725.14   964.9  724.35   977.4  725.38  1045.9  730.99
  1197.8  737.65  1278.8  739.99  1329.4  744.96  1349.6  749.45  1440.8  776.51
  1501.5  790.62  1592.6  808.68  1673.6  829.55    1704  834.35  1795.1  840.92
#Mann= 3 , 0 , 0
       0      .1       0   952.4    .045       0   977.4      .1       0
Bank Sta=952.4,977.4
XS Rating Curve= 0 ,0
Exp/Cntr=0.3,0.1

Type RM Length L Ch R = 1 ,17880.6 ,241.8,248.3,252.6
XS GIS Cut Line= 3
     1564798.756      401761.407     1565738.648      402479.458
     1566443.314      402734.632
#Sta/Elev= 30
    10.1  978.26      91  956.52   131.4  941.86   192.1  915.88   232.5     906
     273  901.97   323.5  904.49   434.7  903.55   495.4  897.66   596.5   860.8
   687.4  823.01   768.3  792.01   869.4  749.57   919.9  732.77     958  723.69
   970.5  722.67     983  723.27  1010.9  726.13  1051.4  737.41  1081.7  742.39
  1223.3   790.8  1304.3  825.04  1486.6  913.01    1517  922.81  1547.4  928.77
  1567.6  929.58    1679  924.69  1739.8  925.09  1820.8  935.36  1932.2  955.58
#Mann= 3 , 0 , 0
       0      .1       0     958    .045       0     983      .1       0
Bank Sta=958,983
XS Rating Curve= 0 ,0
Exp/Cntr=0.3,0.1

Type RM Length L Ch R = 1 ,17632.3 ,311.3,294.6,266
XS GIS Cut Line= 4
     1564561.654      402077.558     1565216.178      402272.767
     1565554.922      402697.633     1566402.162      402810.688
#Sta/Elev= 30
      10   817.4    90.4  826.06   150.7  824.39   200.9  816.95   321.4  791.93
   371.6  785.15   381.7  786.31   431.9  799.82   441.9  800.92   522.3  801.86
   602.7  806.38   642.8  804.87     683  799.69     834  745.55     912  721.37
   924.5  719.72     937  719.99  1025.1  722.93  1135.8  739.93    1166  747.04
    1337  801.74  1477.8  860.23  1588.4  908.73  1668.8  932.24  1769.4  955.87
  1789.5  958.42  1890.1   957.5  1950.4  959.56  2010.7  964.28  2081.1  972.35
#Mann= 3 , 0 , 0
      10      .1       0     912    .045       0     937      .1       0
#XS Ineff= 2 , 0
                         1005.24          744.45
Permanent Ineff=
       F       F
Bank Sta=912,937
XS Rating Curve= 0 ,0
Exp/Cntr=0.3,0.1

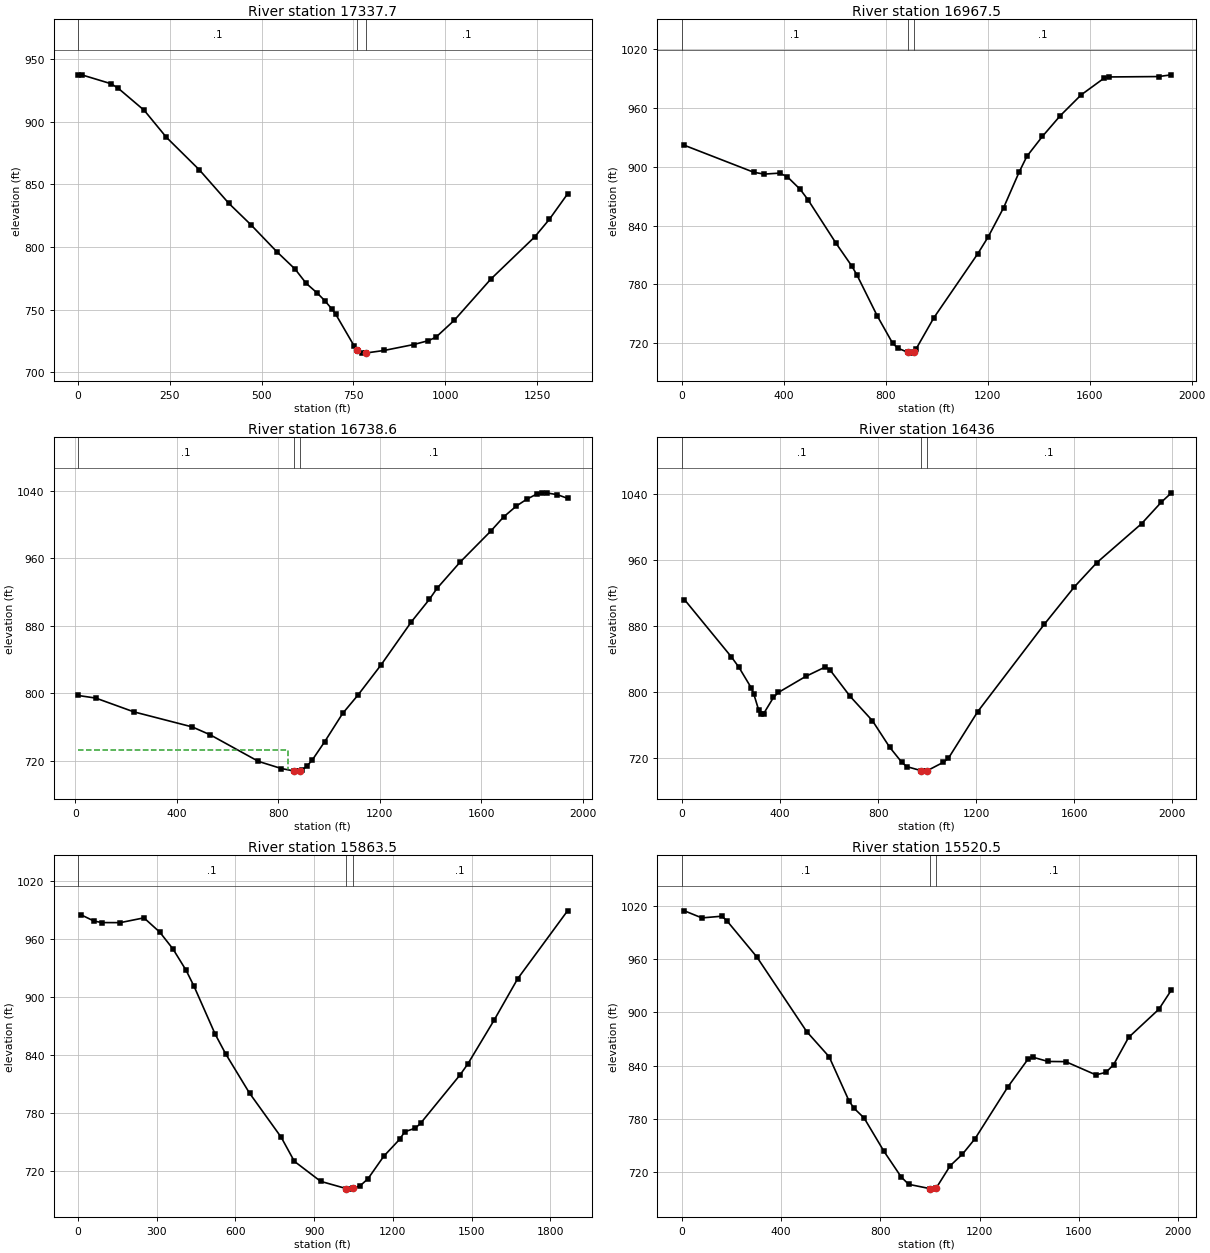
Type RM Length L Ch R = 1 ,17337.7 ,370.8,370.2,369.7
XS GIS Cut Line= 4
     1564503.438       402830.31     1565099.039      402653.648
     1565462.457      402643.553      1565735.02      402860.594
#Sta/Elev= 30
       0  937.23      10  937.23    90.2  930.11   110.2  926.34   180.4  908.88
   240.5  887.47   330.7  861.39   410.8  834.75   470.9  817.68   541.1   796.3
   591.2  782.33   621.2  771.05   651.5  763.24   671.7  757.28   691.9  750.37
     702  746.27   752.5  720.83   760.2  717.75   762.6  716.79   772.7  715.35
   785.2   715.5   833.3  717.46   914.1  722.19   954.5  725.31   974.7  728.02
  1024.6  741.49  1124.2  774.36  1243.6  807.96  1283.5  821.95  1333.2  842.26
#Mann= 3 , 0 , 0
       0      .1       0   760.2    .045       0   785.2      .1       0
Bank Sta=760.2,785.2
XS Rating Curve= 0 ,0
Exp/Cntr=0.3,0.1

Type RM Length L Ch R = 1 ,16967.5 ,230.2,229,227.7
XS GIS Cut Line= 3
     1564492.757      402996.187     1565440.094      402955.997
     1566409.745      402885.694
#Sta/Elev= 30
    10.1  922.03   282.4  894.48   322.8  892.65   383.3  893.65   413.6  889.94
     464   877.1   494.3  866.59   605.2  821.82   665.7  799.07   685.9  790.05
   766.6  747.73   827.1  719.75   847.3  714.89   885.3  710.81   897.8  709.85
   910.3  711.36   917.9  713.78   988.7  746.06  1160.9  811.43  1201.4  828.48
  1262.1  858.35  1322.9  894.68  1353.3  910.79    1414  931.07  1484.9  952.46
  1565.9  973.47  1657.1  990.79  1677.3  991.85  1869.7  992.25  1920.4  994.02
#Mann= 3 , 0 , 0
       0      .1       0   885.3    .045       0   910.3      .1       0
Bank Sta=885.3,910.3
XS Rating Curve= 0 ,0
Exp/Cntr=0.3,0.1

Type RM Length L Ch R = 1 ,16738.6 ,314.5,302.6,290.7
XS GIS Cut Line= 4
     1564515.723      403300.483     1565089.866      403214.362
     1565921.003      403134.673     1566427.613      402997.195
#Sta/Elev= 30
      10  797.35    80.1  794.24   230.2  777.89   460.4  760.02   530.5  750.78
   721.4  719.13   811.9  710.64   859.8  707.85   872.3  707.56   884.8   707.9
   892.4  708.74   912.5   713.5   932.7  720.28     983   742.6  1053.4  775.96
  1113.7  797.71  1204.3  833.32    1325  884.92  1395.4  911.34  1425.6  924.41
  1516.5  955.51  1637.6  992.35  1688.1 1009.15  1738.6 1022.13  1778.9  1030.1
  1819.3 1036.41  1839.5 1037.81  1859.7 1037.61  1900.1 1035.63  1940.4 1031.31
#Mann= 3 , 0 , 0
      10      .1       0   859.8    .045       0   884.8      .1       0
#XS Ineff= 2 , 0
           836.6   732.1
Permanent Ineff=
       F       F
Bank Sta=859.8,884.8
XS Rating Curve= 0 ,0
Exp/Cntr=0.3,0.1

Type RM Length L Ch R = 1 ,16436   ,584.2,572.4,563.8
XS GIS Cut Line= 4
     1564659.259      403977.972     1565353.972      403547.365
     1565778.838      403306.225      1566427.62      403070.826
#Sta/Elev= 30
    10.1  912.32   201.8  842.68   232.1  830.28   282.5  805.27   292.6  798.17
   312.8  778.46   322.9  773.08     333  773.71   373.4  793.56   393.5  799.56
   504.5  818.96   585.3  830.53   605.4  826.27   686.2  794.73     777  765.21
   847.3  733.07   897.1  714.64     917  709.59   974.3  704.79   986.8  704.12
   999.3  704.51  1066.6  714.93  1086.5  719.65  1206.2   776.3  1478.4  882.55
  1600.2  927.62  1691.6  956.98  1874.2 1004.29  1955.4 1030.58    1996 1041.73
#Mann= 3 , 0 , 0
       0      .1       0   974.3    .045       0   999.3      .1       0
Bank Sta=974.3,999.3
XS Rating Curve= 0 ,0
Exp/Cntr=0.3,0.1

Type RM Length L Ch R = 1 ,15863.5 ,314.2,343,371.9
XS GIS Cut Line= 4
     1565040.026      404363.005     1565796.062      403943.524
     1566008.495      403627.745     1566542.448      403311.966
#Sta/Elev= 30
    10.1  985.03    60.3  978.43    90.5  976.79   160.9  976.72   251.3  981.68
   311.7  966.85   361.9  949.47   412.2  927.25   442.4  910.71   522.8  861.26
     563   840.8   653.5  800.33   774.1  754.72   824.4  729.74   924.7  709.02
  1022.4  701.52  1034.9  700.97  1047.4  701.94  1074.9   704.4    1105   711.7
  1165.1     735  1225.2  752.37  1245.2  760.34  1285.2  764.03  1305.2     769
  1455.3  818.95  1485.3  830.43  1585.4  875.69  1675.4  918.65  1865.5  988.95
#Mann= 3 , 0 , 0
       0      .1       0  1022.4    .045       0  1047.4      .1       0
Bank Sta=1022.4,1047.4
XS Rating Curve= 0 ,0
Exp/Cntr=0.3,0.1

Type RM Length L Ch R = 1 ,15520.5 ,296.2,277,257.8
XS GIS Cut Line= 4
     1565089.685      404456.203     1565819.028      404092.801
     1566134.807      404104.284     1566840.613      403644.672
#Sta/Elev= 30
    10.1 1014.32    80.5 1006.36     161 1008.26   181.1 1003.19   301.8  962.48
     503  878.35   593.5     850     674  800.03   694.1  791.94   734.4  781.06
   814.9  743.33     884  714.64   913.6  706.41   999.9  701.51  1012.4  700.96
  1024.9  702.15  1081.5  727.33  1130.9  740.37  1181.6  757.77  1313.5  815.92
  1394.7  847.19    1415  849.46  1475.9   844.7  1546.9   844.5  1668.7  829.61
  1709.3  832.47  1739.7  840.96  1800.6  871.82  1922.4  903.49  1973.1  925.22
#Mann= 3 , 0 , 0
       0      .1       0   999.9    .045       0  1024.9      .1       0
Bank Sta=999.9,1024.9
XS Rating Curve= 0 ,0
Exp/Cntr=0.3,0.1

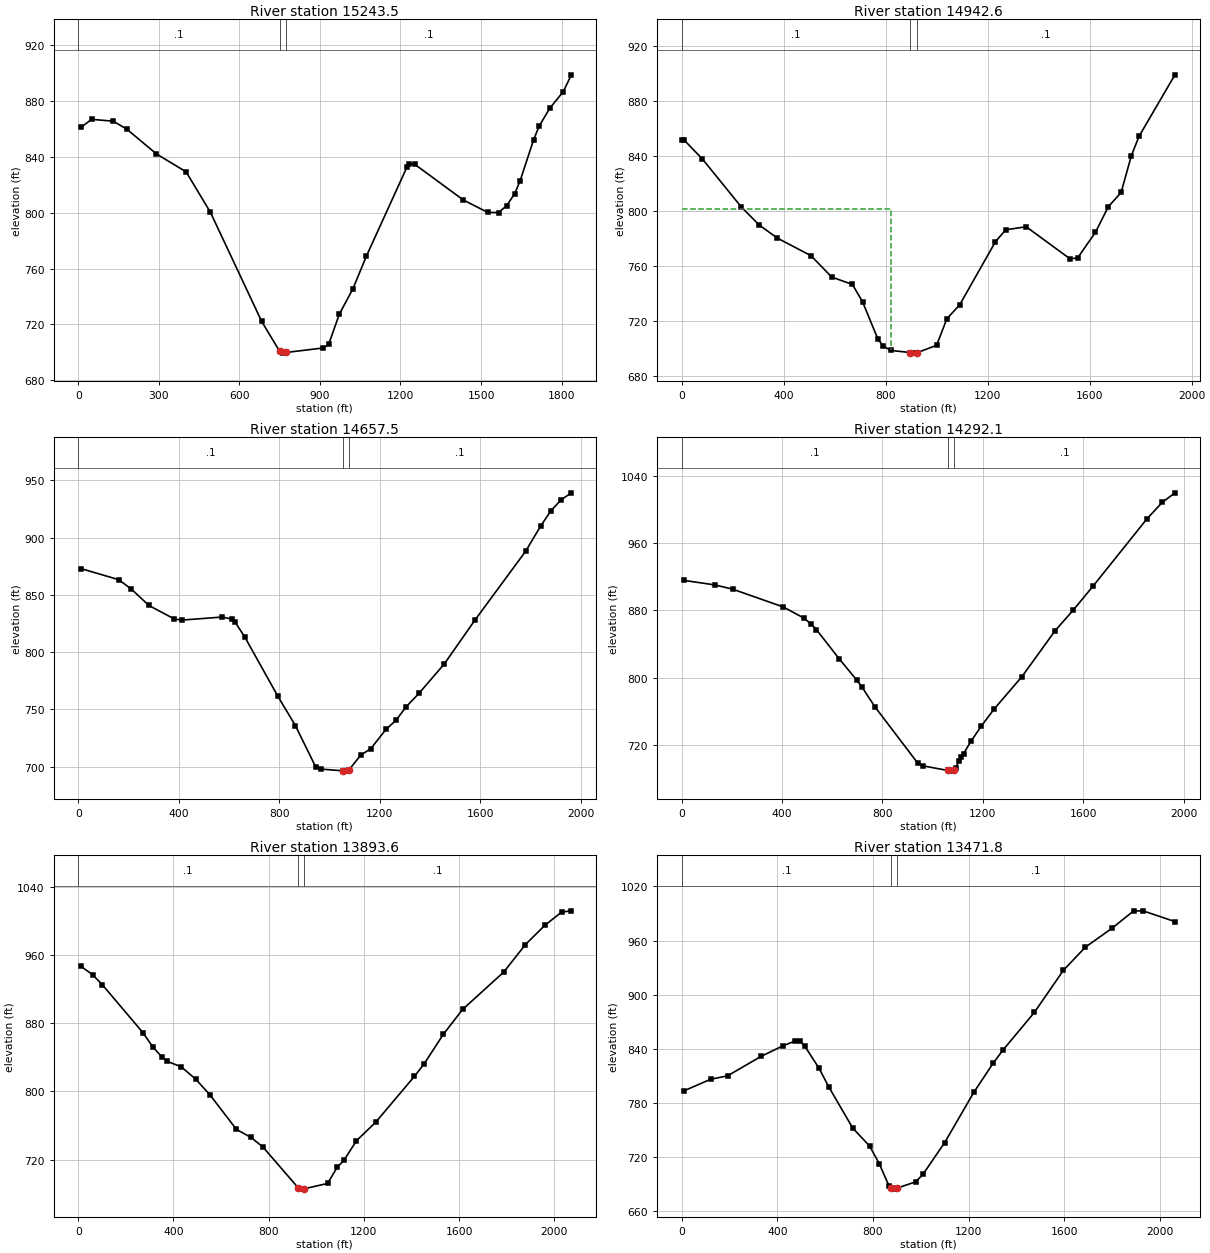
Type RM Length L Ch R = 1 ,15243.5 ,317.8,300.9,284
XS GIS Cut Line= 4
     1565359.714      404787.514     1565928.115       404408.58
     1566180.738      404213.371     1566835.262      403696.642
#Sta/Elev= 30
      10  861.03    50.2  866.78   130.6  865.45   180.8  859.78   291.3  842.03
   401.8  829.21   492.3  800.25   683.1  722.17   750.4  700.63   762.9  699.46
   775.4  699.96   912.6  703.16   932.6  705.72   972.5  727.51  1022.5  745.34
  1072.7  768.72  1223.4  832.33  1233.5  835.01  1253.6  834.52  1434.4     809
  1524.8  800.19    1565  800.07  1595.2  804.99  1625.3  813.56  1645.4  822.76
  1695.6  852.11  1715.7  861.73  1755.9   874.7  1806.2  886.64  1836.3  898.64
#Mann= 3 , 0 , 0
       0      .1       0   750.4    .045       0   775.4      .1       0
Bank Sta=750.4,775.4
XS Rating Curve= 0 ,0
Exp/Cntr=0.3,0.1

Type RM Length L Ch R = 1 ,14942.6 ,279.3,285.1,290.9
XS GIS Cut Line= 4
     1565856.159      405308.615     1566214.529      404743.299
     1566249.861      404314.265     1566885.842      403774.186
#Sta/Elev= 30
       0  851.76    10.1  851.76    81.1  838.15   233.3  803.33   304.2  790.05
   375.2  780.61   507.1   767.8   588.2  752.28   669.3  746.92   709.4   734.2
   769.4  707.14   789.5  702.29   819.5  698.93   897.1  697.39   909.6  696.97
   922.1  697.23   999.7  702.68  1039.8     722  1089.8  732.01  1230.5  778.07
  1270.7  786.69  1351.1  788.86    1522  765.66  1552.2   766.1  1622.6  784.87
  1672.8  803.39  1723.1   813.8  1763.3  840.55  1793.4  854.64  1934.2  899.37
#Mann= 3 , 0 , 0
       0      .1       0   897.1    .045       0   922.1      .1       0
#XS Ineff= 2 , 0
           819.8  802.01
Permanent Ineff=
       F       F
Bank Sta=897.1,922.1
XS Rating Curve= 0 ,0
Exp/Cntr=0.3,0.1

Type RM Length L Ch R = 1 ,14657.5 ,344,365.4,386.8
XS GIS Cut Line= 4
     1565867.837      405356.389      1566427.62      404793.256
     1566571.156      404345.424     1566976.964      403777.893
#Sta/Elev= 30
    10.1  873.02   160.8  863.34   211.1  855.12   281.4  840.76   381.9  829.02
   412.1  827.98   572.9  830.65   613.1  828.81   623.2  826.61   663.4  812.95
     794  761.57   864.1  735.78   944.1  700.04   964.1  697.85  1051.7  696.36
  1064.2  696.05  1076.7  696.99  1124.2  710.04  1164.2  715.68  1224.3  732.54
  1264.3  740.42  1304.7  752.27  1355.3  763.88  1456.4  789.66  1577.8  827.81
    1780  888.12  1840.7  910.48  1881.1  923.55  1921.5  933.15    1962  939.16
#Mann= 3 , 0 , 0
       0      .1       0  1051.7    .045       0  1076.7      .1       0
Bank Sta=1051.7,1076.7
XS Rating Curve= 0 ,0
Exp/Cntr=0.3,0.1

Type RM Length L Ch R = 1 ,14292.1 ,398.8,398.5,398.2
XS GIS Cut Line= 4
     1565949.449      405431.271     1566599.863      404867.894
     1566956.227      404676.974     1567518.736      404258.999
#Sta/Elev= 30
    10.1  915.52   131.6  910.24   202.5  905.22   404.9  884.05   485.9  871.01
   516.3  863.65   536.5   857.3   627.6   822.5   698.5  796.94   718.8  788.86
   769.4  765.82   941.3  698.52   961.6  695.59  1060.2  690.09  1072.7  689.32
  1085.2  690.23  1092.9  692.87  1103.1  701.07  1113.2  706.56  1123.3  710.21
  1153.6  725.08    1194  742.81  1244.6  762.81  1356.2  801.57  1488.2  855.94
  1559.3  879.94  1640.6  909.26  1853.8  988.47  1914.8 1008.06  1965.6 1019.46
#Mann= 3 , 0 , 0
       0      .1       0  1060.2    .045       0  1085.2      .1       0
Bank Sta=1060.2,1085.2
XS Rating Curve= 0 ,0
Exp/Cntr=0.3,0.1

Type RM Length L Ch R = 1 ,13893.6 ,443.9,421.8,407.4
XS GIS Cut Line= 3
      1565985.53      405608.539     1566961.573      405063.103
     1567566.699       404325.84
#Sta/Elev= 30
    10.1  946.87    60.4  936.83   100.7  925.24     272  868.83   312.3  852.54
   352.6  839.94   372.7  835.33   433.1  828.72   493.6  814.32     554   795.7
   664.8  755.37   725.3  746.03   775.6  734.87   924.3  686.84   936.8  685.33
   949.3  685.72  1047.6  691.97  1087.9  710.82  1118.1   719.8  1168.8     742
    1250  763.85  1412.4  817.55    1453  832.12  1534.1  866.92  1615.3  896.15
  1787.8   939.9  1879.1  972.19  1960.3  994.66  2031.3 1010.29  2071.9 1011.69
#Mann= 3 , 0 , 0
       0      .1       0   924.3    .045       0   949.3      .1       0
Bank Sta=924.3,949.3
XS Rating Curve= 0 ,0
Exp/Cntr=0.3,0.1

Type RM Length L Ch R = 1 ,13471.8 ,717.3,700.8,686.5
XS GIS Cut Line= 4
     1566461.021      406030.462     1567007.505      405568.349
     1567133.816      405183.673     1567637.488      404386.179
#Sta/Elev= 30
    10.1  793.32     121  806.09   191.5  809.86   332.6  831.55   423.4  843.18
   473.8  848.49   493.9  848.46   514.1   843.1   574.6  818.24   614.9  797.79
   715.7   751.8   786.5  731.89     827  712.13   867.5  687.54   875.3  685.39
   887.8  684.17   900.3  685.18   978.9  692.28  1009.2  700.48  1100.3  735.82
    1222  791.48  1303.1  823.89  1343.7   838.3  1475.5  880.21  1597.2  927.01
  1688.5  952.51  1800.1  973.55  1891.4  992.96  1931.9  992.79  2063.8  981.03
#Mann= 3 , 0 , 0
       0      .1       0   875.3    .045       0   900.3      .1       0
Bank Sta=875.3,900.3
XS Rating Curve= 0 ,0
Exp/Cntr=0.3,0.1

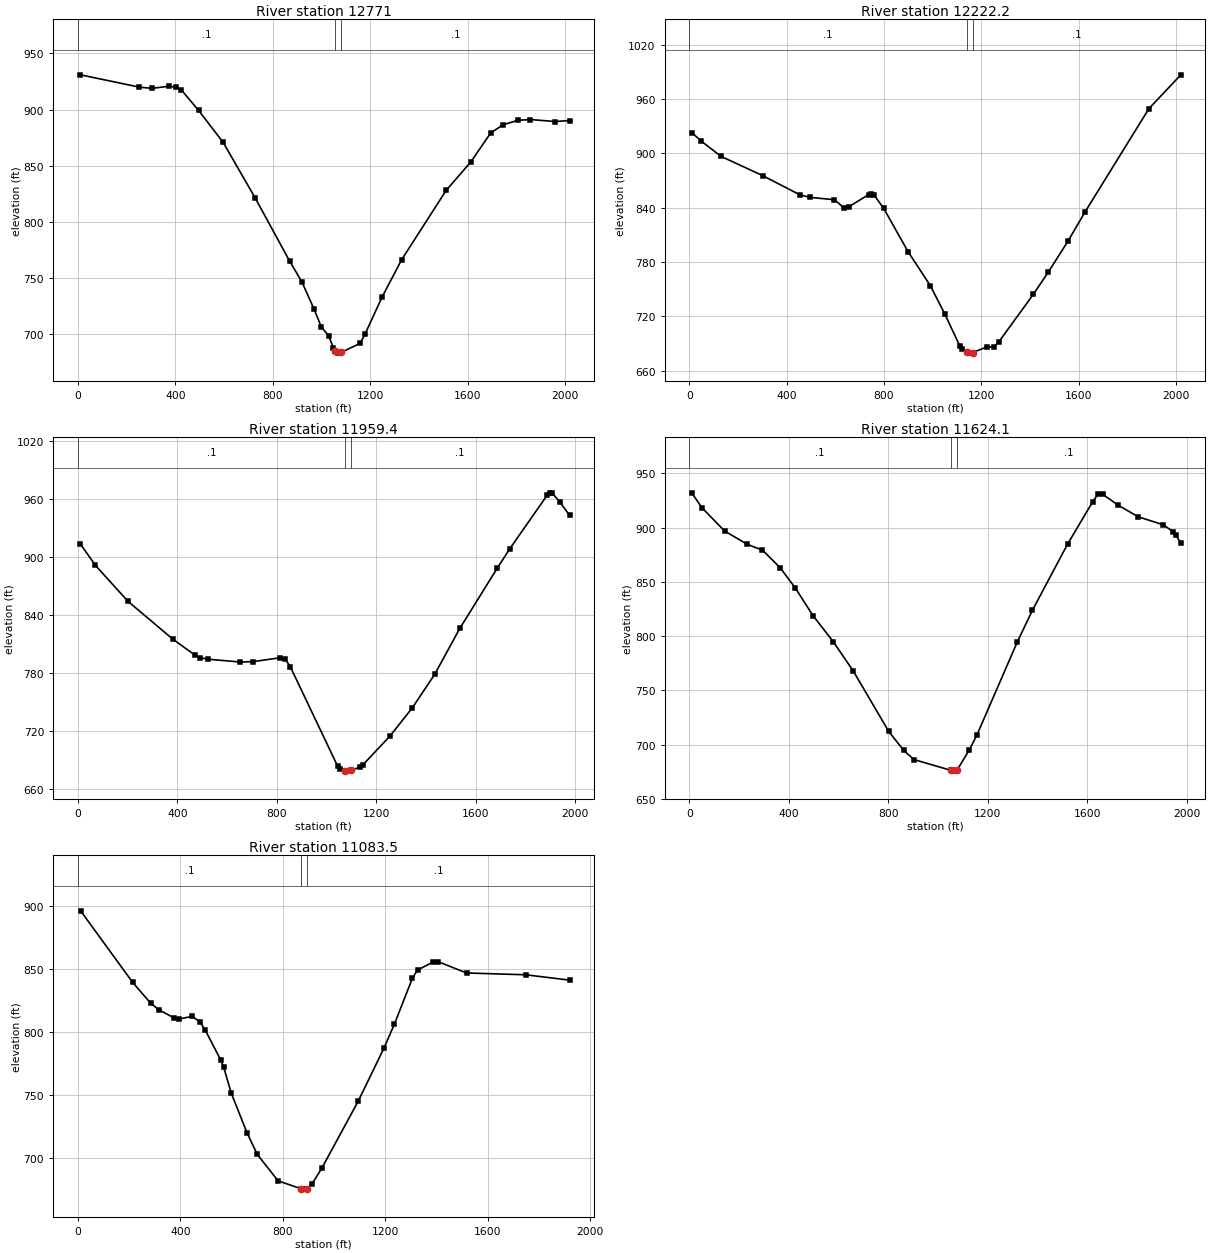
Type RM Length L Ch R = 1 ,12771   ,510.9,548.9,586.8
XS GIS Cut Line= 4
     1567383.059      406332.605     1567782.598      405505.193
     1567690.735      405189.414     1567845.531       404435.16
#Sta/Elev= 30
    10.1  930.92   252.4  919.93   302.9  918.87   373.6  920.73   403.9  919.75
   424.1  917.49   494.8  899.24   595.7  870.73     727  821.25   868.3  765.01
   918.8  746.39   968.7  722.19   998.6  706.28  1028.4  698.39  1048.4  687.71
  1055.8  684.97  1068.3   682.9  1080.8  683.65    1158  691.62  1177.9  699.78
  1247.7  732.79  1328.7  766.31  1511.1     828  1612.4  853.36  1693.5  879.07
  1744.1  886.38  1804.9  890.36  1855.6  891.09  1956.9  889.32  2017.7  890.14
#Mann= 3 , 0 , 0
       0      .1       0  1055.8    .045       0  1080.8      .1       0
Bank Sta=1055.8,1080.8
XS Rating Curve= 0 ,0
Exp/Cntr=0.3,0.1

Type RM Length L Ch R = 1 ,12222.2 ,257.7,262.8,267.8
XS GIS Cut Line= 3
     1567469.632      406372.957     1568046.704      405568.349
     1568951.982      405078.386
#Sta/Elev= 30
    10.1  923.02    50.5  913.29   131.3  896.58   303.1  875.26   454.7  854.22
   495.1  851.44   596.1   848.8   636.5  839.76   656.7  841.23   737.6  854.51
   747.7   855.6   757.8  854.57   798.2  839.61   899.2   791.4   990.2  754.07
  1050.7  722.28  1111.3  687.53  1121.3  684.07  1139.1  680.95  1151.6  679.45
  1164.1  680.05  1222.3  686.27  1252.5  686.31  1272.7  692.21    1414  744.47
  1474.6  768.73  1555.3  802.78  1625.9  835.27  1888.3  949.33  2019.5  986.69
#Mann= 3 , 0 , 0
       0      .1       0  1139.1    .045       0  1164.1      .1       0
Bank Sta=1139.1,1164.1
XS Rating Curve= 0 ,0
Exp/Cntr=0.3,0.1

Type RM Length L Ch R = 1 ,11959.4 ,330.3,335.3,342.9
XS GIS Cut Line= 4
      1567528.49      406459.502     1568075.411      405803.748
     1568608.804      405630.572     1569090.777      405341.185
#Sta/Elev= 30
      10  913.58    70.3  891.52   200.9  854.47   381.7  815.27   472.2  798.48
   492.2  796.21   522.4  794.65     653  791.71   703.2   792.1   813.7  796.15
   833.8  794.57   853.9  786.74  1044.2  683.99  1054.2  681.27  1071.7   679.3
  1084.2  678.94  1096.7  679.75  1134.3  683.07  1144.3  685.08  1254.5   715.2
  1344.6  744.42  1434.8   779.2  1535.2  826.44  1685.7  888.68  1735.9  908.63
  1886.5   964.1  1896.6  966.61  1906.6  966.39  1936.7  957.44  1976.9  943.24
#Mann= 3 , 0 , 0
       0      .1       0  1071.7    .045       0  1096.7      .1       0
Bank Sta=1071.7,1096.7
XS Rating Curve= 0 ,0
Exp/Cntr=0.3,0.1

Type RM Length L Ch R = 1 ,11624.1 ,598.4,540.6,515.9
XS GIS Cut Line= 4
     1567577.379      406544.949      1568190.24      406027.664
     1568827.848      405999.905     1569337.615       405833.82
#Sta/Elev= 30
    10.2  932.12    50.8  918.47   142.1  896.99   233.5  884.59   294.4  879.34
   365.5   863.1   426.4  844.48   497.4  819.01   578.6  795.06   659.9  767.77
     802  712.21   862.8  694.65   903.3  686.29  1052.9  676.27  1065.4  675.61
  1077.9  676.94  1126.2  695.29  1156.5  708.85  1318.6   794.5  1379.4  823.74
  1521.1  884.87  1622.3  923.99  1642.5  930.63  1662.7  930.66  1723.4  920.87
  1804.4   910.1  1905.5  902.66    1946  896.21  1956.1  893.57  1976.3  885.47
#Mann= 3 , 0 , 0
       0      .1       0  1052.9    .045       0  1077.9      .1       0
Bank Sta=1052.9,1077.9
XS Rating Curve= 0 ,0
Exp/Cntr=0.3,0.1

Type RM Length L Ch R = 1 ,11083.5 ,11066.2,11083.5,11091
XS GIS Cut Line= 3
     1567774.927       406985.87      1568526.15      406502.522
     1569382.311      405934.909
#Sta/Elev= 30
    10.2  895.96   213.2  839.29   284.2  822.63   314.7  817.67   375.6  810.92
   395.9  810.25   446.6  812.22   477.1  807.73   497.4  801.18   558.3  777.36
   568.5  772.34   598.9  751.22   659.8  720.08   700.4  702.72   781.6  681.79
   870.6  675.58   883.1  675.21   895.6  675.53   913.4     679   953.7  692.28
  1094.7  745.03  1195.4  787.17  1235.7  805.96  1306.2   842.4  1326.3  848.99
  1386.8   855.3  1406.9  855.63  1517.7  846.66  1749.3  845.23  1920.5  840.98
#Mann= 3 , 0 , 0
       0      .1       0   870.6    .045       0   895.6      .1       0
Bank Sta=870.6,895.6
XS Rating Curve= 0 ,0
Exp/Cntr=0.3,0.1

Chan Stop Cuts=-1
Use User Specified Reach Order=0